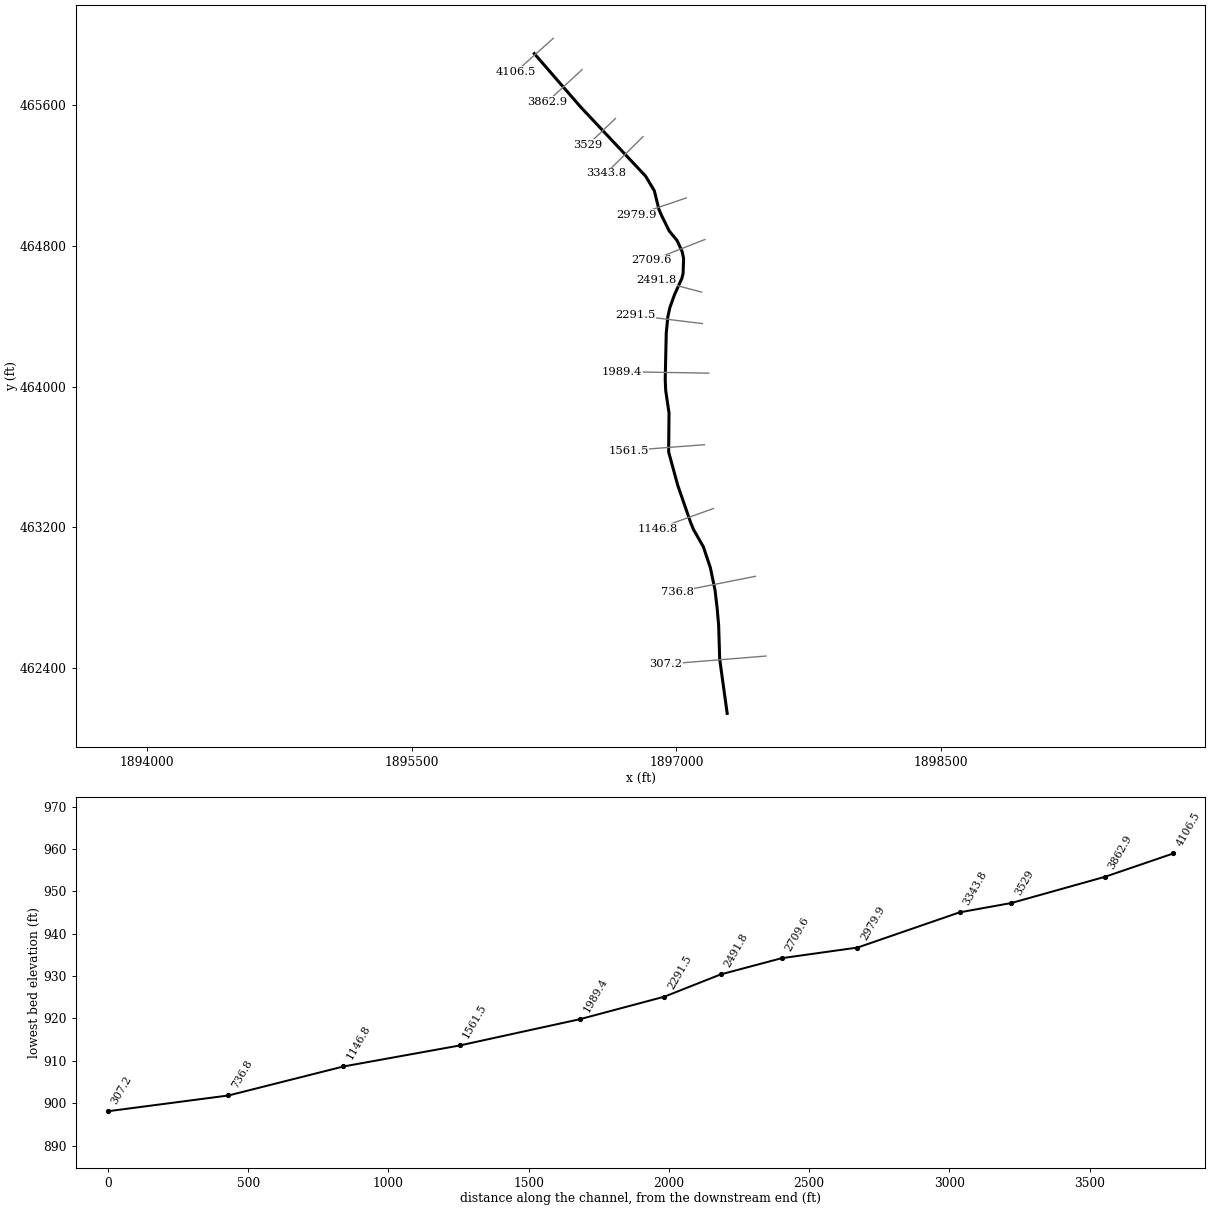
--- LAURELFK2.prj (project) ---

Proj Title=LAURELFK2
Current Plan=p01
Default Exp/Contr=0,0
English Units
Geom File=g01
Flow File=f01
Plan File=p01
BEGIN DESCRIPTION:
END DESCRIPTION:
DSS Export Rating Curves= 0
DSS Export Rating Curve Sorted= 0
DSS Export Volume Flow Curves= 0
DXF OffsetX= 0
DXF OffsetY= 0
DXF ScaleX= 0
DXF ScaleY= 0

--- LAURELFK2.p01 (plan) ---

Plan Title=Floodplain
Program Version=4.00
Geom File=g01
Flow File=f01
K Sum by GR=0
Std Step Tol=0.01
Critical Tol=0.01
Num of Std Step Trials=20
Max Error Tol=0.3
Flow Tol Ratio=0.001
Split Flow NTrial=30
Split Flow Tol=0.02
Split Flow Ratio=0.02
Log Output Level=0
Friction Slope Method=1
Unsteady Friction Slope Method=2
Unsteady Bridges Friction Slope Method=1
Global Log Level=0
CheckData=False
Run HTab=0
Run UNet=0
Run PostProcess=0
UNET Theta=0
UNET Theta Warmup=0
UNET ZTol=0
UNET ZSATol=0
UNET MxIter=0
UNET MaxInSteps=0
UNET DtIC=0
UNET DtMin=0
UNET MaxCRTS=0
UNET WFStab=0
UNET SFStab=0
UNET WFX=0
UNET SFX=0
UNET DSS MLevel=0
UNET DZMax Abort=0
UNET Convert EG Bridges=0
UNET Use Existing IB Tables=0
UNET Froude Limit=0
UNET Froude Power=0
Write IC File=0
Echo Input=False
Echo Output=False
Write Detailed=0

--- LAURELFK2.f01 (steady flow) ---

Flow Title=NFF Regression Equation
Program Version=4.10
Number of Profiles= 1
Profile Names=P100yr
River Rch & RM=LAURELFK2,Main            ,4106.5
603.8667
River Rch & RM=LAURELFK2,Main            ,307.2
664.8575
Boundary for River Rch & Prof#=LAURELFK2,Main            , 1
Up Type= 0
Dn Type= 3
Dn Slope=0.0087
DSS Import GetInterval= 0
DSS Import GetPeak= 0
DSS Import FillOption= 0

--- LAURELFK2.g01 (geometry) ---

Geom Title=USGS 10m DEM
Program Version=4.10

River Reach=LAURELFK2       ,Main
Reach XY= 30
     1896194.369      465891.026     1896455.673      465589.347
     1896825.217       465195.01     1896874.658      465112.023
     1896900.478      465006.729     1896913.933      464975.045
     1896958.725      464884.149     1897003.815      464829.082
     1897031.902      464767.482     1897040.496      464727.899
     1897037.631      464642.482     1897030.867       464615.28
      1896988.59      464521.026     1896962.823      464449.433
     1896951.149      464395.943      1896942.21      464304.418
     1896936.285       464040.93     1896939.081      463977.115
     1896957.857      463850.577     1896955.774      463628.181
     1897007.336      463439.379     1897080.243       463228.17
     1897096.389      463188.847     1897152.604       463089.82
     1897192.222      462971.139     1897218.806      462843.095
     1897230.962       462737.65     1897239.183      462642.062
     1897245.085      462451.728     1897287.442      462144.093

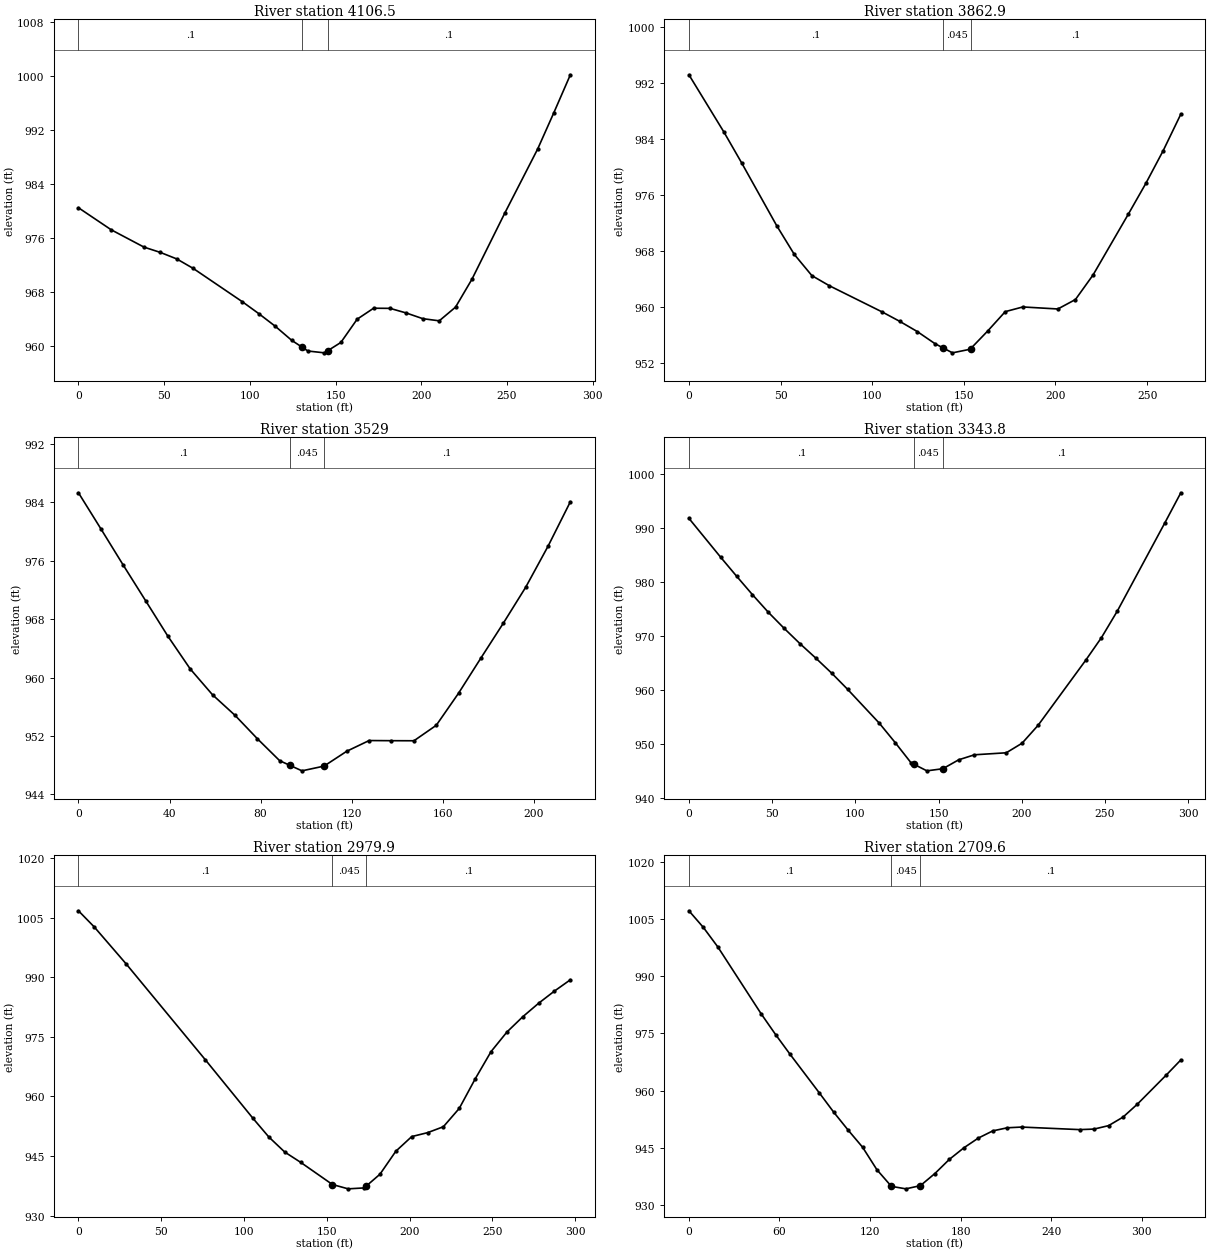
Type RM Length L Ch R = 1 ,4106.5  ,243.3,243.6,244
XS GIS Cut Line= 2
     1896301.927      465977.764     1896088.179      465786.255
#Sta/Elev= 27
       0  980.47    19.1   977.2    38.3  974.62    47.8  973.84    57.4  972.87
      67  971.46    95.7  966.51   105.2  964.76   114.8  962.89   124.4   960.8
   130.6  959.76   133.9  959.21   143.5  958.94   145.6  959.28   153.1  960.48
   162.6  963.93   172.2  965.56   181.8  965.54   191.3  964.85   200.9  964.01
   210.5  963.69     220  965.72   229.6  969.87   248.7  979.65   267.9  989.17
   277.4  994.59     287  1000.2
#Mann= 3 , 0 , 0
       0      .1       0   130.6    .045       0   145.6      .1       0
Bank Sta=130.6,145.6
XS Rating Curve= 0 ,0
Exp/Cntr=0.3,0.1

Type RM Length L Ch R = 1 ,3862.9  ,333.6,334,334.3
XS GIS Cut Line= 2
     1896465.575      465800.458     1896268.527      465618.166
#Sta/Elev= 25
       0  993.12    19.2   984.9    28.8  980.53    47.9  971.58    57.5  967.48
    67.1  964.45    76.7     963   105.5  959.26     115  957.93   124.6  956.47
   134.2  954.75   138.7  954.13   143.8  953.43   153.4  953.94   153.7  954.02
     163  956.54   172.6  959.31   182.2  959.98   201.3  959.69   210.9  961.04
   220.5  964.54   239.7   973.2   249.3  977.61   258.8   982.3   268.4   987.5
#Mann= 3 , 0 , 0
       0      .1       0   138.7    .045       0   153.7      .1       0
Bank Sta=138.7,153.7
XS Rating Curve= 0 ,0
Exp/Cntr=0.3,0.1

Type RM Length L Ch R = 1 ,3529    ,184.7,185.2,185.6
XS GIS Cut Line= 2
     1896653.981       465522.19     1896497.731      465372.884
#Sta/Elev= 24
       0  985.33     9.8  980.42    19.6  975.46    29.5  970.55    39.3  965.68
    49.1   961.2    58.9  957.66    68.8  954.84    78.6  951.64    88.4  948.63
    92.9  947.99    98.2  947.24   107.9  947.89   117.9  949.93   127.7  951.39
   137.5  951.37   147.4  951.36   157.2  953.48     167  957.88   176.8  962.69
   186.6  967.44   196.5   972.4   206.3  978.01   216.1   984.1
#Mann= 3 , 0 , 0
       0      .1       0    92.9    .045       0   107.9      .1       0
Bank Sta=92.9,107.9
XS Rating Curve= 0 ,0
Exp/Cntr=0.3,0.1

Type RM Length L Ch R = 1 ,3343.8  ,373.7,363.9,353.2
XS GIS Cut Line= 2
     1896810.107      465419.165     1896600.384      465210.831
#Sta/Elev= 26
       0  991.74    19.1  984.54    28.6  981.06    38.1  977.65    47.7  974.37
    57.2   971.4    66.8  968.54    76.3  965.87    85.8   963.1    95.4   960.1
   114.4  953.85     124  950.24   133.5  946.51   135.2  946.25     143  945.03
   152.6  945.42   162.1  947.07   171.6     948   190.7  948.37   200.2  950.14
   209.8  953.44   238.4  965.47   247.9  969.67   257.5  974.62   286.1  990.96
   295.6  996.47
#Mann= 3 , 0 , 0
       0      .1       0   135.2    .045       0   152.6      .1       0
Bank Sta=135.2,152.6
XS Rating Curve= 0 ,0
Exp/Cntr=0.3,0.1

Type RM Length L Ch R = 1 ,2979.9  ,269.1,270.2,271.2
XS GIS Cut Line= 2
     1897055.246      465071.248     1896773.996      464975.415
#Sta/Elev= 25
       0 1006.79     9.6 1002.69    28.8  993.41    76.7  969.21   105.4  954.49
     115  949.78   124.6  945.99   134.2   943.4   153.4  937.81   162.9  936.72
   172.5  936.95   173.9  937.45   182.1   940.4   191.7   946.2   201.3  949.89
   210.9  950.88   220.4  952.37     230  956.99   239.6  964.41   249.2   971.3
   258.8  976.24   268.4   980.1     278  983.51   287.5  986.56   297.1   989.4
#Mann= 3 , 0 , 0
       0      .1       0   153.4    .045       0   173.9      .1       0
Bank Sta=153.4,173.9
XS Rating Curve= 0 ,0
Exp/Cntr=0.3,0.1

Type RM Length L Ch R = 1 ,2709.6  ,232.1,217.9,203.4
XS GIS Cut Line= 2
     1897161.611      464835.455     1896858.226      464716.097
#Sta/Elev= 28
       0 1007.18     9.6  1002.8    19.2  997.67    47.9  980.13    57.5  974.67
    67.1  969.49    86.3  959.46    95.9  954.37   105.5  949.64   115.1  945.14
   124.6  939.23   134.2  934.87   143.8  934.22   153.4  935.06     163  938.23
   172.6  941.95   182.2  944.98   191.8  947.54   201.4  949.43     211  950.24
   220.5  950.43   258.9  949.76   268.5   949.9   278.1   950.8   287.7  953.04
   297.2  956.44   316.4   964.1     326  968.04
#Mann= 3 , 0 , 0
       0      .1       0   134.2    .045       0   153.4      .1       0
Bank Sta=134.2,153.4
XS Rating Curve= 0 ,0
Exp/Cntr=0.3,0.1

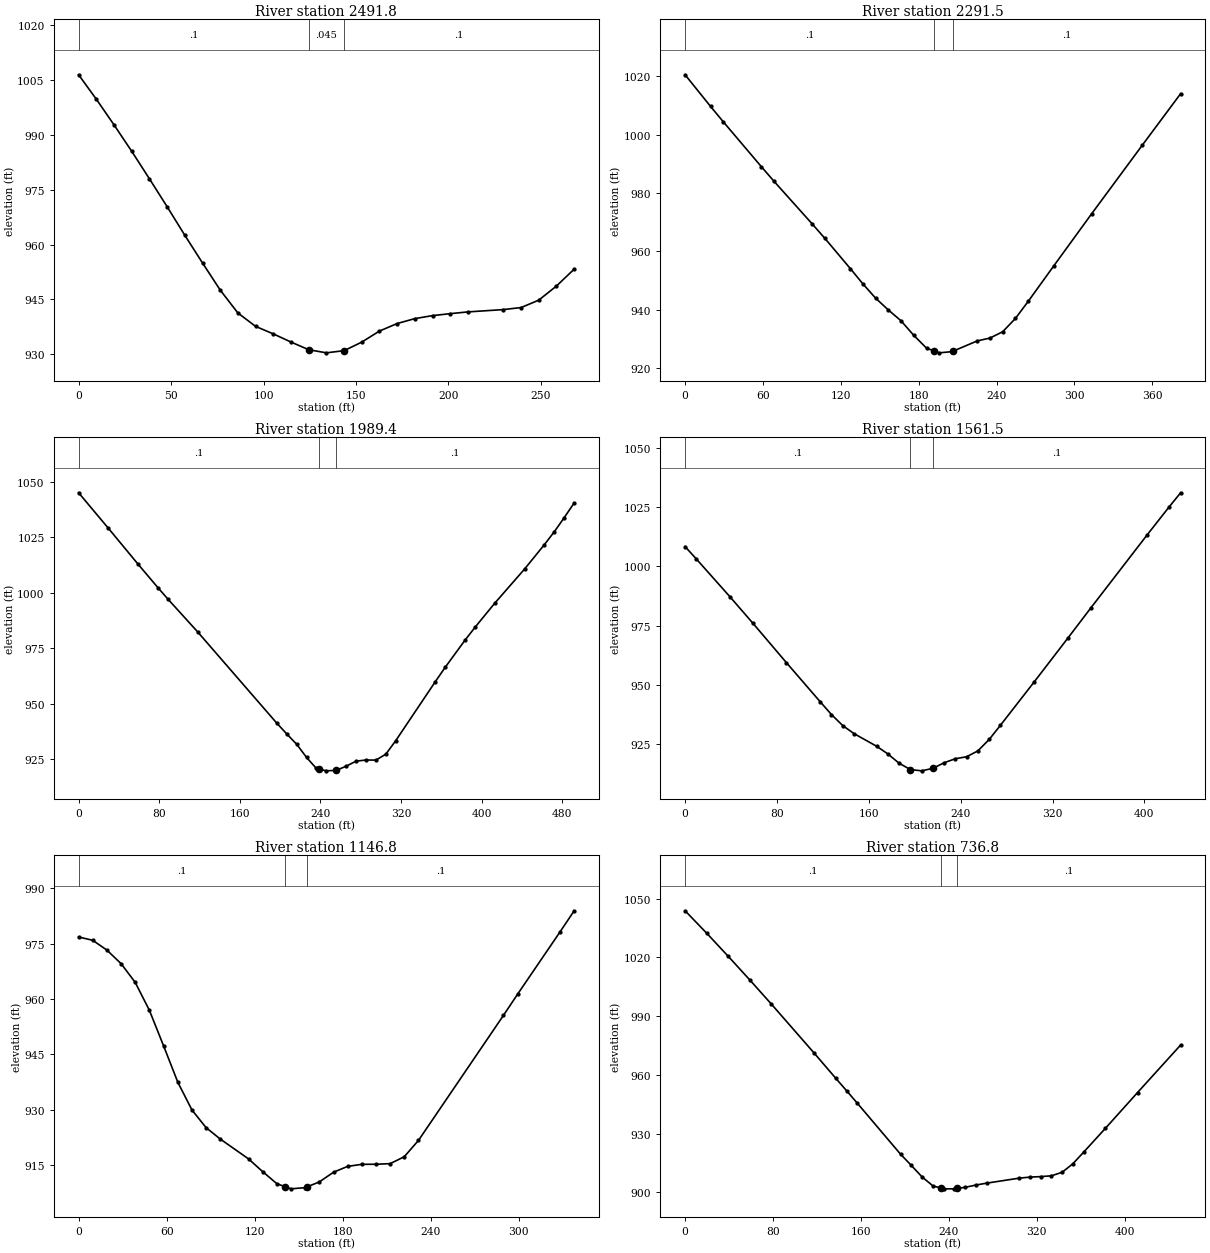
Type RM Length L Ch R = 1 ,2491.8  ,196.9,200.2,203.1
XS GIS Cut Line= 2
     1897142.746      464536.526     1896883.718      464605.276
#Sta/Elev= 28
       0 1006.44     9.6  999.74    19.1  992.77    28.7  985.52    38.3  977.98
    47.9  970.32    57.4  962.56      67  954.96    76.6  947.53    86.1   941.3
    95.7  937.62   105.3  935.56   114.9  933.32   124.4  931.24     134  930.38
   143.6  930.98   153.1  933.31   162.7  936.34   172.3   938.4   181.8  939.74
   191.4  940.56     201   941.1   210.6  941.58   229.7  942.21   239.3  942.77
   248.8  944.78   258.4  948.64     268  953.28
#Mann= 3 , 0 , 0
       0      .1       0   124.4    .045       0   143.6      .1       0
Bank Sta=124.4,143.6
XS Rating Curve= 0 ,0
Exp/Cntr=0.3,0.1

Type RM Length L Ch R = 1 ,2291.5  ,299.6,302.1,304.4
XS GIS Cut Line= 2
     1897147.173       464357.88     1896768.223      464404.277
#Sta/Elev= 27
       0 1020.54    19.6 1009.69    29.4 1004.42    58.7  989.04    68.5     984
    97.9  969.38   107.7  964.41   127.3  954.05     137   948.8   146.8  943.89
   156.6  939.85   166.4  936.12   176.2  931.13     186  926.76   191.6  925.83
   195.8  925.14   205.6  925.55   206.6  925.74   225.2  929.25   234.9  930.21
   244.7  932.38   254.5  936.94   264.3  942.77   283.9  954.88   313.2  972.83
   352.4  996.47   381.8 1014.06
#Mann= 3 , 0 , 0
       0      .1       0   191.6    .045       0   206.6      .1       0
Bank Sta=191.6,206.6
XS Rating Curve= 0 ,0
Exp/Cntr=0.3,0.1

Type RM Length L Ch R = 1 ,1989.4  ,425.8,428,430
XS GIS Cut Line= 2
     1897183.546       464076.28     1896691.664      464084.616
#Sta/Elev= 30
       0 1045.04    29.5 1029.07      59 1012.89    78.7 1002.32    88.6  997.18
   118.1  982.43   196.8  941.26   206.6  936.44   216.5  931.78   226.3  925.84
   236.1  920.87   239.1  920.55     246  919.81   255.8  920.04   265.6  921.89
   275.5  924.18   285.3  924.68   295.2  924.65     305  927.32   314.8  933.37
   354.2  960.01     364  966.47   383.7   978.7   393.6  984.47   413.2  995.34
   442.8 1010.72   462.4 1021.67   472.3 1027.51   482.1 1033.84     492 1040.46
#Mann= 3 , 0 , 0
       0      .1       0   239.1    .045       0   255.8      .1       0
Bank Sta=239.1,255.8
XS Rating Curve= 0 ,0
Exp/Cntr=0.3,0.1

Type RM Length L Ch R = 1 ,1561.5  ,408.4,414.7,420.5
XS GIS Cut Line= 2
     1897158.531      463670.002     1896728.185       463636.89
#Sta/Elev= 27
       0 1008.35     9.8 1003.11    39.2  987.08    58.9  976.06    88.3  959.29
   117.7  942.78   127.5  937.39   137.3  932.74   147.1  929.35   166.8  924.01
   176.6  920.76   186.4  916.83   196.2  914.17     206  913.62   215.8  914.67
   225.6  917.04   235.4  918.74   245.2  919.57     255  922.05   264.9   926.9
   274.7   932.9   304.1  951.22   333.5  969.77   353.1  982.26   402.2 1013.15
   421.8 1025.25   431.6 1031.08
#Mann= 3 , 0 , 0
       0      .1       0   196.2    .045       0   215.8      .1       0
Bank Sta=196.2,215.8
XS Rating Curve= 0 ,0
Exp/Cntr=0.3,0.1

Type RM Length L Ch R = 1 ,1146.8  ,413,409.9,406.2
XS GIS Cut Line= 2
     1897209.403      463307.528     1896891.695      463192.945
#Sta/Elev= 30
       0  976.76     9.6  975.87    19.3  973.21      29  969.52    38.6  964.46
    48.2  956.95    57.9  947.32    67.6  937.48    77.2     930    86.8  925.23
    96.5  922.13   115.8  916.75   125.4  913.32   135.1  910.05   140.6  909.26
   144.8  908.66   154.4  908.99   155.6  909.18     164  910.53   173.7  913.15
   183.3  914.73     193  915.29   202.6  915.31   212.3  915.47   221.9  917.34
   231.6  921.76   289.5  955.56   299.1  961.27   328.1  978.16   337.7  983.85
#Mann= 3 , 0 , 0
       0      .1       0   140.6    .045       0   155.6      .1       0
Bank Sta=140.6,155.6
XS Rating Curve= 0 ,0
Exp/Cntr=0.3,0.1

Type RM Length L Ch R = 1 ,736.8   ,431.7,429.6,426.6
XS GIS Cut Line= 2
     1897447.388      462922.365     1897004.976      462834.872
#Sta/Elev= 30
       0 1043.74    19.6 1032.33    39.2 1020.53    58.8 1008.49    78.4   996.2
   117.6  971.02   137.2   958.2   147.1  951.81   156.9  945.42   196.1  919.49
   205.9  913.76   215.7  907.88   225.5  903.35   232.9  902.19   235.3  901.82
   245.1  901.83   247.9  902.05   254.9   902.6   264.7  903.76   274.5  904.73
   303.9  907.26   313.7   907.8   323.5  908.06   333.3  908.46   343.1  910.26
   352.9  914.61   362.7  920.52   382.4  932.63   411.8  950.98     451  975.22
#Mann= 3 , 0 , 0
       0      .1       0   232.9    .045       0   247.9      .1       0
Bank Sta=232.9,247.9
XS Rating Curve= 0 ,0
Exp/Cntr=0.3,0.1

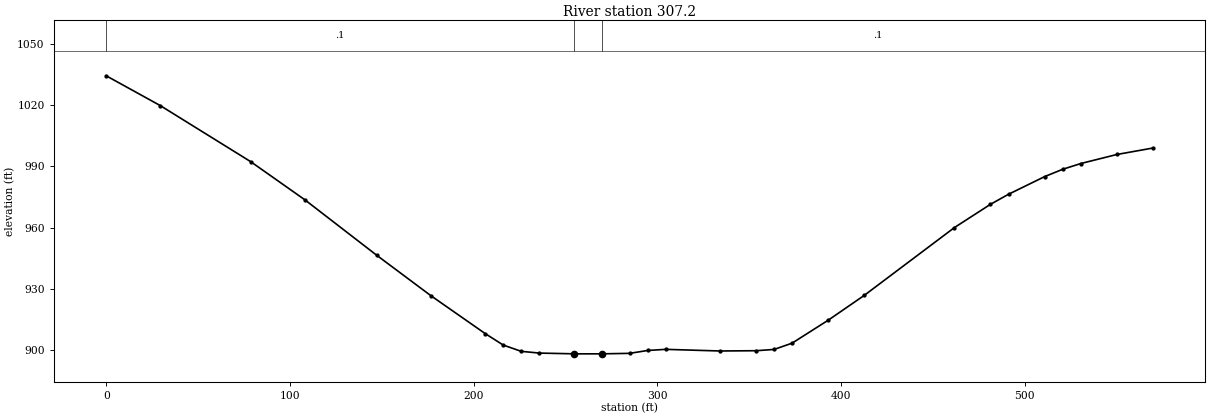
Type RM Length L Ch R = 1 ,307.2   ,306,307.2,308.5
XS GIS Cut Line= 2
     1897506.857      462469.658      1896938.97      462423.613
#Sta/Elev= 30
       0 1034.43    29.5 1019.78    78.6  992.35   108.1  973.64   147.4  946.32
   176.8  926.56   206.3  908.02   216.1   902.4   225.9  899.33   235.8  898.47
   254.7  898.11   255.4   898.1   269.7   898.1   284.9  898.34   294.7  899.75
   304.5   900.3     334   899.5   353.6  899.63   363.5  900.25   373.3  903.33
   392.9  914.54   412.6  926.76   461.7  960.02   481.3  971.41   491.2  976.37
   510.8     985   520.6  988.58   530.5  991.42   550.1  995.84   569.8  999.02
#Mann= 3 , 0 , 0
       0      .1       0   254.7    .045       0   269.7      .1       0
Bank Sta=254.7,269.7
XS Rating Curve= 0 ,0
Exp/Cntr=0.3,0.1

Chan Stop Cuts=-1
Use User Specified Reach Order=0
Composite Channel Slope=5